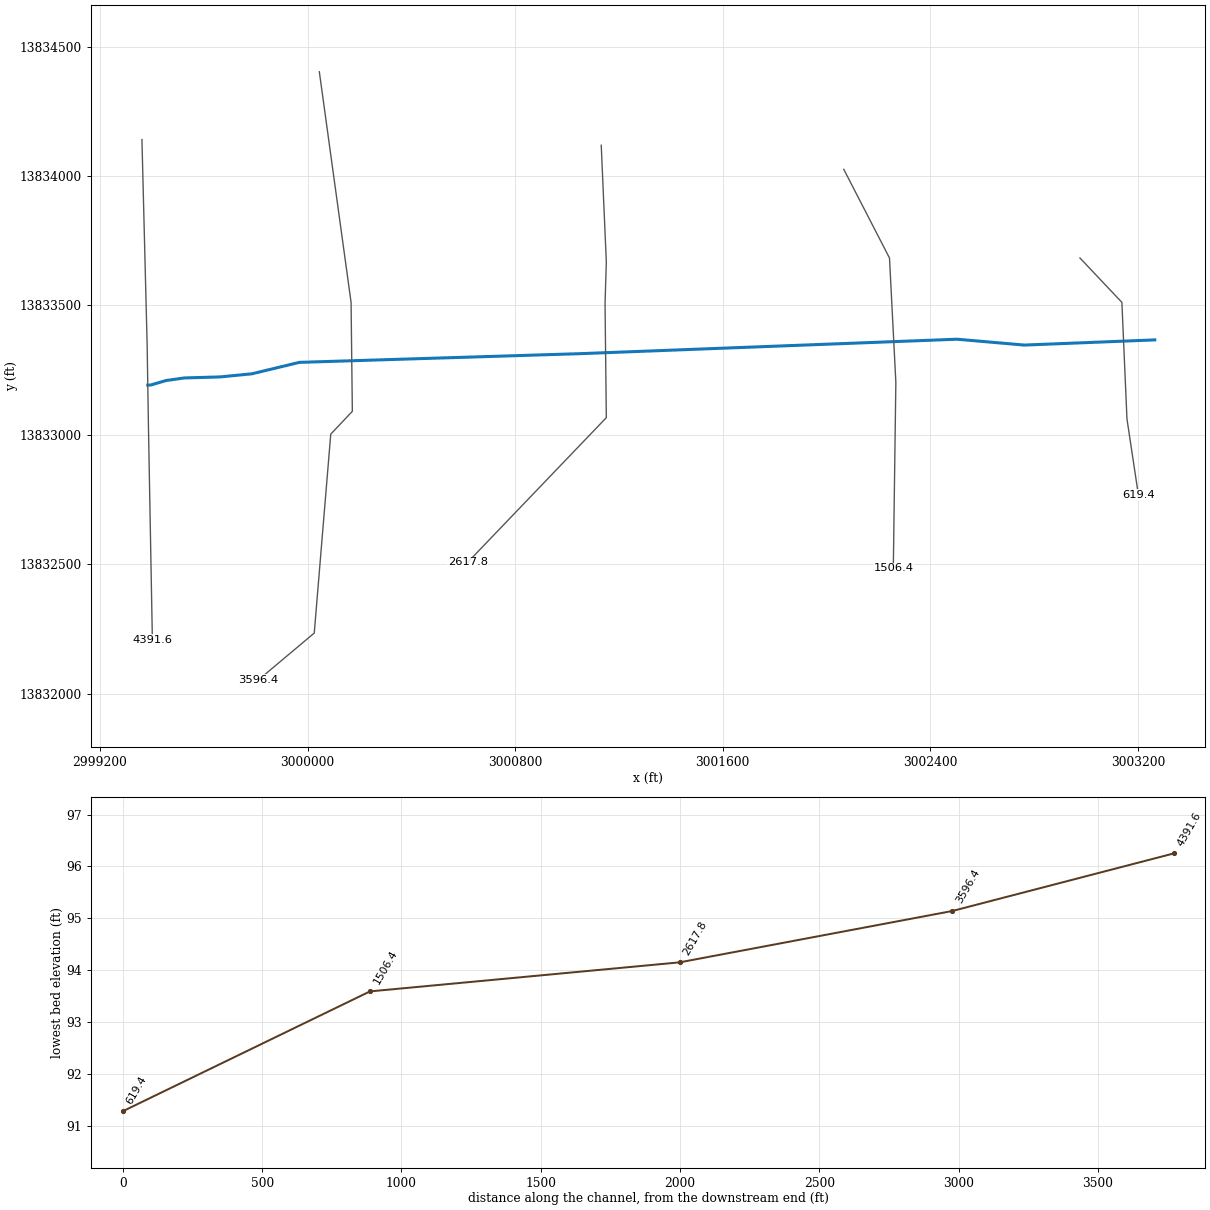
--- T103-01-00.PRJ (project) ---

Proj Title=T103-01-00
Current Plan=p02
Default Exp/Contr=.3,.1
English Units
Geom File=g01
Flow File=f01
Flow File=f02
Plan File=p01
Plan File=p02
Y Axis Title=Elevation
X Axis Title(PF)=Main Channel Distance
X Axis Title(XS)=Station
BEGIN DESCRIPTION:
HCFCD Unit T103-01-00
Flood Hazard Model
10, 2, 1, 0.2% Event
Filename T103-00-01.prj
Prepared by:  Watershed Concepts  Date:
Reviewed by:                      Date:
STATUS FINAL
END DESCRIPTION:
DSS Export Rating Curves= 0
DSS Export Rating Curve Sorted= 0
DSS Export Volume Flow Curves= 0
DXF OffsetX= 0
DXF OffsetY= 0
DXF ScaleX= 1
DXF ScaleY= 10

--- T103-01-00.p02 (plan) ---

Plan Title=Floodway
Version=Version 3.0.1  Mar 2001
Short Identifier=Floodway0607
Geom File=g01
Flow File=f02
Subcritical Flow
K Sum by GR= 0
Std Step Tol= 0.01
Critical Tol= 0.01
Num of Std Step Trials= 20
Max Error Tol= 0.3
Flow Tol Ratio= 0.001
Split Flow NTrial= 30
Split Flow Tol= 0.02
Split Flow Ratio= 0.02
Log Output Level= 0
Friction Slope Method= 1
Unsteady Friction Slope Method= 2
Parabolic Critical Depth
Global Vel Dist= 0 , 0 , 0
Global Log Level= 0
CheckData=True
Encroach Param=-1 ,0,0, 2
Encroach River=T103-01-00
Encroach Reach=Reach - 1
Encroach Node=4391.6
       1  4942.1  5046.1
Encroach Node=3596.4
       1  4888.6  5111.4
Encroach Node=2617.8
       1 4888.55 5111.45
Encroach Node=1506.4
       1  4886.5  5113.4
Encroach Node=619.4
       1  4955.5  5065.2
Encroach Reach=T103-01-00_0006
Encroach Node=4391.6
       1  4942.1  5046.1
Encroach Node=3596.4
       1  4888.6  5111.4
Encroach Node=2617.8
       1 4888.55 5111.45
Encroach Node=1506.4
       1  4886.5  5113.4
Encroach Node=619.4
       1  4955.5  5065.2
Computation Interval=1HOUR
Output Interval=1HOUR
Run HTab= 0
Run UNet= 0
Run PostProcess= 0
UNET Theta= 1
UNET ZTol= 0.02
UNET ZSATol= 0.1
UNET MxIter= 20
UNET MaxInSteps= 20
UNET DtIC= 0
UNET DtMin= 0
UNET MaxCRTS= 20
UNET WFStab= 2
UNET SFStab= 1
UNET WFX= 1
UNET SFX= 1
UNET Convert EG Bridges=-1
UNET Use Existing IB Tables=-1
Instantaneous Interval=1HOUR
Write IC File= 0
IC Time=0
Write Velocity= 0
Write Detailed= 0

--- T103-01-00.p01 (plan) ---

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Plan Title=FEMA Effective June 2007
Program Version=3.13
Short Identifier=FEMAeff0607
Geom File=g01
Flow File=f01
Unsteady Bridges Friction Slope Method= 1
Encroach Param=-1 ,0,0, 0
UNET Theta Warmup= 1
UNET DSS MLevel= 4
UNET DZMax Abort= 100
UNET Froude Reduction=False
UNET Froude Limit= 1
UNET Froude Power= 10
Echo Input=False
Echo Output=False
Detailed Automatic Start=False, 10

--- T103-01-00.f02 (steady flow) ---

Flow Title= Floodway
Program Version=3.13
Number of Profiles= 2
Profile Names=1PCT_100yr,1PCTFloodway_100yrFW
River Rch & RM=T103-01-00,T103-01-00_0006       ,4391.6
    1019    1019
River Rch & RM=T103-01-00,T103-01-00_0006       ,2617.8
    1102    1102
River Rch & RM=T103-01-00,T103-01-00_0006       ,1506.4
    1129    1129
River Rch & RM=T103-01-00,T103-01-00_0006       ,619.4
    1138    1138
Boundary for River Rch & Prof#=T103-01-00,T103-01-00_0006       , 1
Up Type= 0
Dn Type= 3
Dn Slope=0.0026
Boundary for River Rch & Prof#=T103-01-00,T103-01-00_0006       , 2
Up Type= 0
Dn Type= 1
Dn Known WS=99.11
DSS Import GetInterval= 0
DSS Import GetPeak= 0
DSS Import FillOption= 0

--- T103-01-00.f01 (steady flow) ---

Flow Title=FEMA Effective June 2007
Program Version=3.13
Number of Profiles= 4
Profile Names=10PCT_10yr,2PCT_50yr,1PCT_100yr,0.2PCT_500yr
River Rch & RM=T103-01-00,T103-01-00_0006       ,4391.6
     542     853    1019    1505
River Rch & RM=T103-01-00,T103-01-00_0006       ,2617.8
     585     923    1102    1627
River Rch & RM=T103-01-00,T103-01-00_0006       ,1506.4
     600     946    1129    1668
River Rch & RM=T103-01-00,T103-01-00_0006       ,619.4
     605     953    1138    1682
Boundary for River Rch & Prof#=T103-01-00,T103-01-00_0006       , 1
Up Type= 0
Dn Type= 3
Dn Slope=0.0026
Boundary for River Rch & Prof#=T103-01-00,T103-01-00_0006       , 2
Up Type= 0
Dn Type= 3
Dn Slope=0.0026
Boundary for River Rch & Prof#=T103-01-00,T103-01-00_0006       , 3
Up Type= 0
Dn Type= 3
Dn Slope=0.0026
Boundary for River Rch & Prof#=T103-01-00,T103-01-00_0006       , 4
Up Type= 0
Dn Type= 3
Dn Slope=0.0026
DSS Import GetInterval= 0
DSS Import GetPeak= 0
DSS Import FillOption= 0

--- T103-01-00.g01 (geometry) ---

Geom Title=T103-01-00 June 2007
Version=Version 3.0.1  Mar 2001

River Reach=T103-01-00      ,T103-01-00_0006
Reach XY= 11
      2999384.51     13833192.36      2999396.75       13833193.
       2999454.5       13833210.      2999524.75       13833220.
      2999662.75       13833224.       2999785.5       13833236.
      2999968.72      13833280.2      3001049.23     13833313.74
      3002502.34     13833369.63       3002762.5       13833347.
        3003265.       13833367.

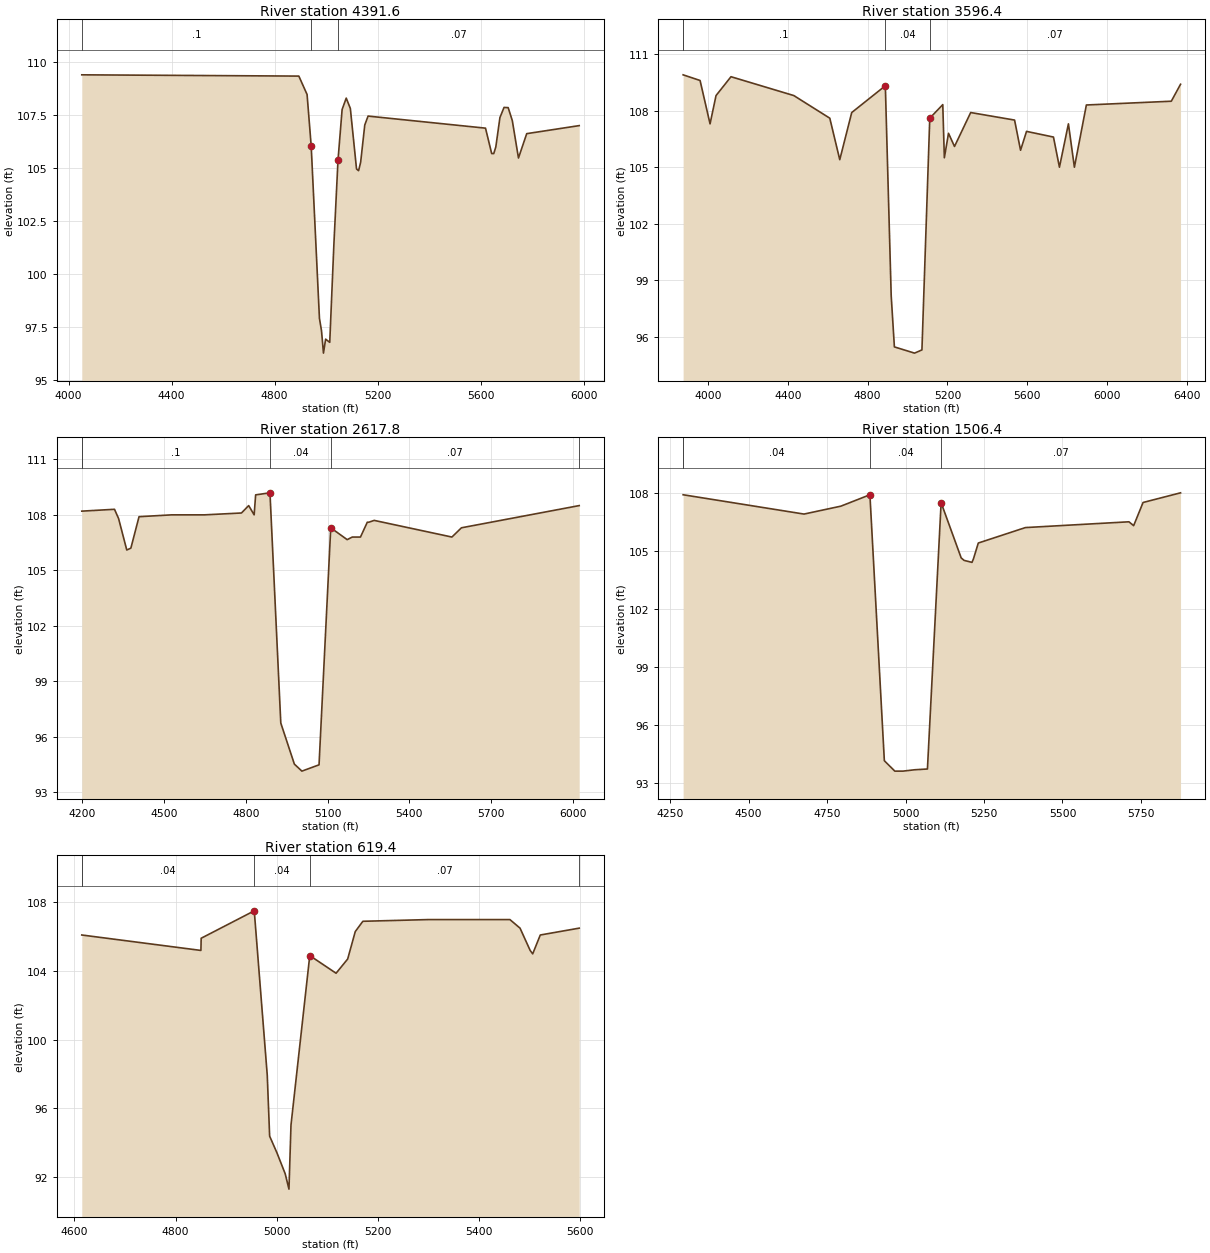
Type RM Length L Ch R = 1 ,4391.6  ,793,795.2,796.1
BEGIN DESCRIPTION:
Cross Section 4391.6-Interpolated
END DESCRIPTION:
XS GIS Cut Line= 4
      2999361.93      13834140.8      2999382.04     13833346.29
      2999387.07     13833029.49      2999402.16     13832209.83
#Sta/Elev= 30
  4051.3   109.4  4894.1  109.34  4926.1  108.47  4942.1  106.03  4974.1   97.89
  4982.1   97.31  4989.7   96.25  4998.1   96.91  5014.1   96.76  5030.1  101.37
  5046.1  105.36  5062.1  107.76  5078.1   108.3  5094.1  107.81  5118.1  104.95
  5126.1  104.87  5134.1  105.27  5150.1  107.03  5162.9  107.45  5618.9  106.88
  5642.9  105.68  5650.9  105.68  5658.9  105.99  5674.9  107.38  5690.9  107.86
  5706.9  107.85  5722.9  107.24  5746.9  105.47  5778.9  106.62  5982.7     107
#Mann= 3 , 1 , 0
  4051.3      .1       0  4942.1     .04       0  5046.1     .07       0
Bank Sta=4942.1,5046.1
XS Rating Curve= 0
Exp/Cntr=.3,.1

Type RM Length L Ch R = 1 ,3596.4  ,977.3,978.6,979.9
BEGIN DESCRIPTION:
Cross Section 3596.4
END DESCRIPTION:
XS GIS Cut Line= 6
      3000045.53     13834402.57      3000167.87     13833511.94
      3000172.76     13833091.09      3000089.57     13833003.01
      3000025.96     13832234.72      2999810.64     13832053.65
#Sta/Elev= 30
  3874.7   109.9  3959.7   109.6  4009.7   107.3  4039.7   108.8  4114.7   109.8
  4429.7   108.8  4610.1   107.6  4660.1   105.4  4720.1   107.9  4888.6  109.32
    4918   98.18    4934   95.47    5035   95.14  5072.1   95.31  5111.4   107.6
  5176.6  108.32  5184.5   105.5  5205.4   106.8  5235.4   106.1  5316.6   107.9
  5536.6   107.5  5566.6   105.9  5596.6   106.9  5731.6   106.6  5761.6     105
  5806.6   107.3  5836.6     105  5896.6   108.3  6322.5   108.5  6368.8   109.4
#Mann= 4 , 1 , 0
  3874.7      .2       0  3874.7      .1       0  4888.6     .04       0
  5111.4     .07       0
Bank Sta=4888.6,5111.4
XS Rating Curve= 0
Exp/Cntr=.3,.1

Type RM Length L Ch R = 1 ,2617.8  ,1110.3,1111.4,1113.2
BEGIN DESCRIPTION:
Cross Section 2617.8
END DESCRIPTION:
XS GIS Cut Line= 5
       3001131.9     13834118.74      3001151.48     13833668.53
      3001146.58     13833507.04      3001151.48     13833066.62
      3000618.08     13832508.76
#Sta/Elev= 27
  4198.3   108.2  4318.3   108.3  4333.3   107.8  4363.3   106.1  4378.3   106.2
  4408.3   107.9  4528.3     108  4648.9     108  4783.9   108.1  4810.5   108.5
  4830.5     108 4836.05  109.08 4888.55  109.19 4928.25   96.75 4978.05   94.53
 5005.65   94.15 5068.55   94.49 5111.45   107.3 5171.75  106.66  5190.5   106.8
  5220.5   106.8  5245.5   107.6  5250.9   107.6  5270.9   107.7  5555.9   106.8
  5590.9   107.3  6022.8   108.5
#Mann= 5 , 1 , 0
  4198.3      .2       0  4198.3      .1       0 4888.55     .04       0
 5111.45     .07       0  6022.8      .2       0
Bank Sta=4888.55,5111.45
XS Rating Curve= 0
Exp/Cntr=.3,.1

Type RM Length L Ch R = 1 ,1506.4  ,889.5,887,886.8
BEGIN DESCRIPTION:
Cross Section 1506.4
END DESCRIPTION:
XS GIS Cut Line= 4
      3002066.57     13834025.76      3002242.74     13833683.21
      3002267.21     13833203.64      3002257.42     13832484.29
#Sta/Elev= 21
  4291.4   107.9  4676.6   106.9  4794.1  107.31  4886.5   107.9  4886.6  107.87
  4932.5   94.13  4965.8   93.59  4991.9   93.59    5029   93.66  5069.8    93.7
  5113.4  107.49  5177.3  104.63  5186.8   104.5  5211.8   104.4  5216.8   104.6
  5231.8   105.4  5381.8   106.2  5711.8   106.5  5726.8   106.3  5756.8   107.5
  5876.2     108
#Mann= 4 , 1 , 0
  4291.4      .2       0  4291.4     .04       0  4886.5     .04       0
  5113.4     .07       0
Bank Sta=4886.5,5113.4
XS Rating Curve= 0
Exp/Cntr=.3,.1

Type RM Length L Ch R = 1 ,619.4   ,0,0,0
BEGIN DESCRIPTION:
Cross Section 619.4
END DESCRIPTION:
XS GIS Cut Line= 4
      3002976.78     13833683.21      3003138.27     13833511.94
      3003157.84     13833061.73      3003201.88     13832768.12
#Sta/Elev= 23
  4614.7   106.1  4850.1   105.2  4850.6  105.91  4955.5  107.51  4981.2   97.92
  4985.9   94.37  4999.4   93.46  5000.7   93.37  5016.6   92.18  5024.1   91.28
  5028.1   95.02  5065.2   104.9  5117.2  103.87  5140.1   104.7  5155.1   106.3
  5170.1   106.9  5300.7     107  5460.7     107  5480.7   106.5  5500.7   105.2
  5505.7     105  5520.7   106.1  5597.6   106.5
#Mann= 5 , 1 , 0
  4614.7      .2       0  4614.7     .04       0  4955.5     .04       0
  5065.2     .07       0  5597.6      .2       0
Bank Sta=4955.5,5065.2
XS Rating Curve= 0
Exp/Cntr=.3,.1

Chan Stop Cuts=-1